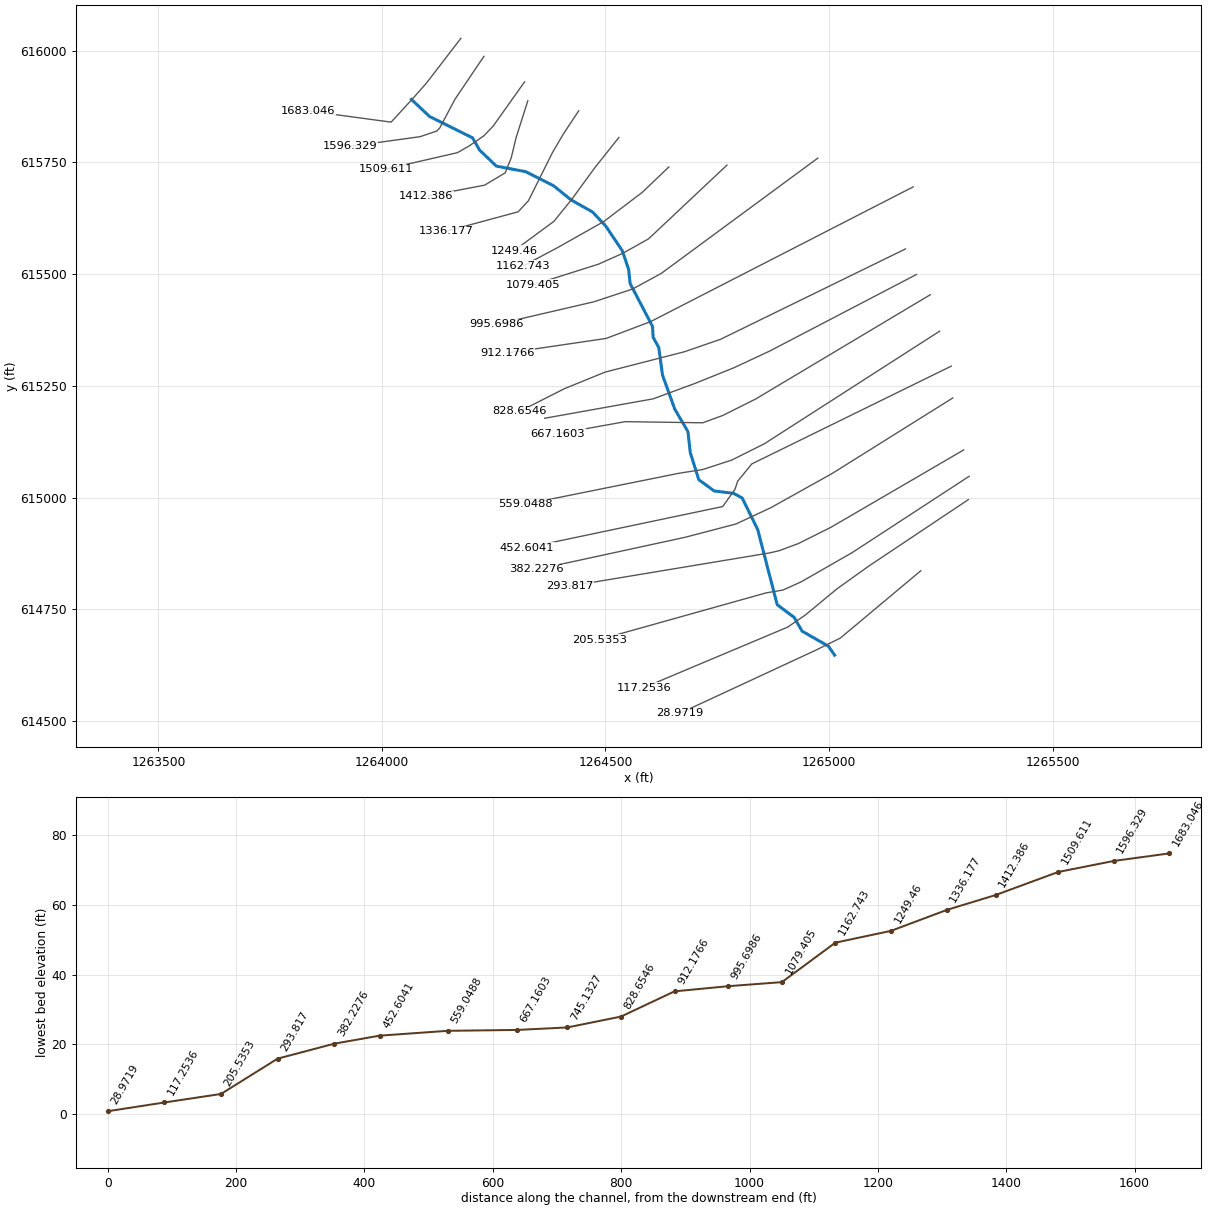
--- 512_ras.prj (project) ---

Proj Title=512
Current Plan=p01
Default Exp/Contr=0.3,0.1
English Units
Geom File=g01
Flow File=f01
Plan File=p01
Y Axis Title=Elevation
X Axis Title(PF)=Main Channel Distance
X Axis Title(XS)=Station
BEGIN DESCRIPTION:
RFD model 512 exported to HEC-RAS
END DESCRIPTION:

--- 512_ras.p01 (plan) ---

Plan Title=Plan 01
Program Version=4.10
Short Identifier=Plan 01
Geom File=g01
Flow File=f01
Subcritical Flow
Calc Critical at every XS
Secant Critical Depth

--- 512_ras.f01 (steady flow) ---

Flow Title=Flow 01
Program Version=5.01
Number of Profiles= 5
Profile Names=10yr,25yr,50yr,100yr,500yr
River Rch & RM=512,20,1683.046
  559.44  705.13  851.21  959.94 1209.04
River Rch & RM=512,20,1509.611
   562.4  709.41  856.53   966.7 1218.78
River Rch & RM=512,20,1412.386
  564.37  712.25  860.06  971.19 1225.24
River Rch & RM=512,20,1336.177
  566.32  715.08  863.57  975.65 1231.68
River Rch & RM=512,20, 1249.46
  577.83  731.76  884.31 1002.06 1269.85
River Rch & RM=512,20,1162.743
  580.19  735.18  888.56 1007.48 1277.71
River Rch & RM=512,20,995.6986
  582.06   737.9  891.94  1011.8 1283.97
River Rch & RM=512,20,912.1766
  587.16  745.32  901.17 1023.59 1301.09
River Rch & RM=512,20,745.1327
  590.83  750.66  907.82 1032.09 1313.44
River Rch & RM=512,20,559.0488
   592.2  752.66   910.3 1035.26 1318.05
River Rch & RM=512,20,452.6041
  593.56  754.64  912.77 1038.42 1322.66
River Rch & RM=512,20, 293.817
  654.42  843.96 1024.12 1182.05 1533.73
River Rch & RM=512,20,205.5353
  661.38  854.27 1036.99 1198.78 1558.57
River Rch & RM=512,20, 28.9719
  663.68  857.67 1041.24 1204.31  1566.8
Boundary for River Rch & Prof#=512,20,1
Up Type= 0
Dn Type= 2
Boundary for River Rch & Prof#=512,20,2
Up Type= 0
Dn Type= 2
Boundary for River Rch & Prof#=512,20,2
Up Type= 0
Dn Type= 2
Boundary for River Rch & Prof#=512,20,2
Up Type= 0
Dn Type= 2
Boundary for River Rch & Prof#=512,20,2
Up Type= 0
Dn Type= 2

--- 512_ras.g01 (geometry) ---

Geom Title=512
Program Version=4.10

River Reach=512,20
Reach XY= 30
1264065.86614433615890.8777402191264106.69946447615852.544417083
1264202.53276816615805.0444283341264218.36609605615777.544436052
1264255.86608386615741.7111122761264321.69939744615729.211114049
 1264384.1993781615697.5444549771264423.36603221 615665.87779659
1264470.86601743615639.2111364161264500.03267461615608.377811402
1264537.53266194615552.5444935411264551.69932321 615510.87783885
1264555.03265458615479.211181462  1264605.032637615383.377875119
1264606.69930249 615358.377882541264619.19929808615335.877888843
 1264627.5326272615274.2112402171264654.93687779615198.095670581
1264684.45076665615147.7484483721264689.65910003615100.873448372
1264708.75632223615040.1095594611264743.06490868615015.098139953
1264786.59197038615009.7131474471264805.68919262 614999.29648076
 1264840.4114148 614928.983980761264884.10354447614760.595670596
1264922.29798889614731.9498372381264939.65910003614701.567892805
1264998.68687779614667.7137261481265012.57576671614647.748448357

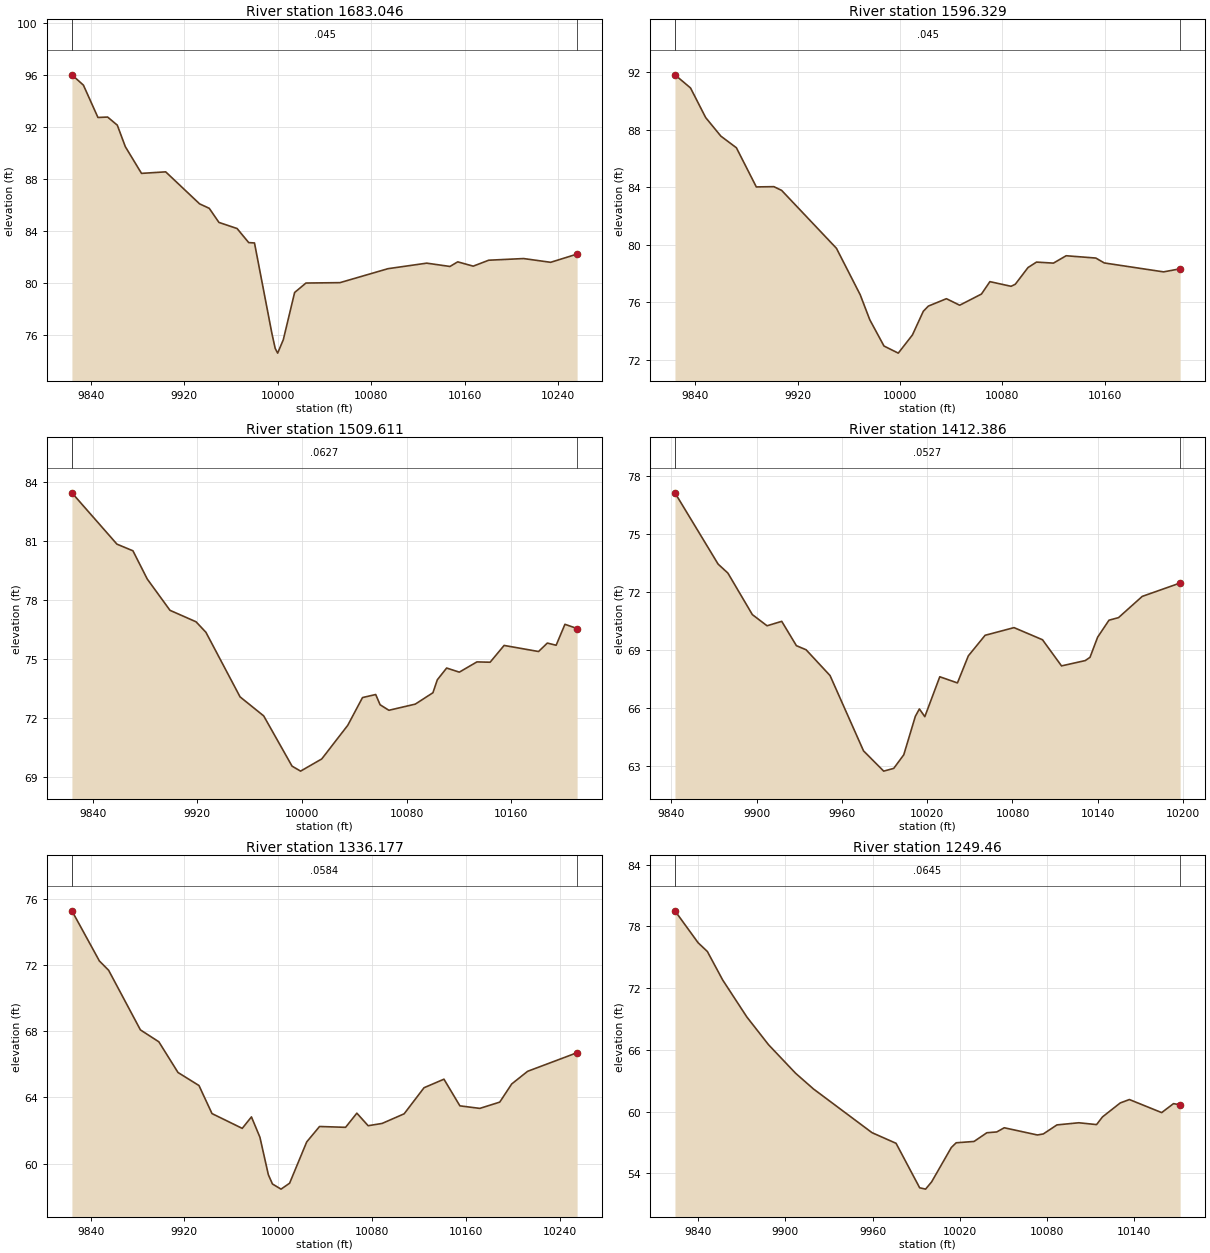
Type RM Length L Ch R = 1 ,1683.046,86.717200,86.717200,86.717200
XS GIS Cut Line= 6
1264176.49273211616027.5347615631264099.70788303615927.695107877
1264067.27965331615890.9223773181264065.91078144615889.464231282
1264020.41720188 615840.091474981263834.21928519  615865.2650861
#Sta/Elev= 30
9824.01995.98619 9833.8595.193579846.26792.712079854.54592.743339862.82392.12165
9869.68790.469039883.51788.419049904.21288.536499933.18486.080149941.46285.73604
 9949.7484.653799965.25884.184919975.17983.105459980.13983.07691 9995.0276.13234
9997.84474.982889999.948 74.618310004.7875.6484710014.4679.2740610024.15 80.0003
 10053.280.0287710094.3481.1023410127.4481.5266510147.3181.2723710153.93 81.6274
10167.17 81.296210180.4281.7519910210.2181.8797610233.3981.5918710256.0382.22334
#Mann= 3 , 0 , 0
9824.019   0.045       09824.019   0.045       010256.03   0.045       0
#XS Ineff= 2 , 0
       0                10059.41       0
Bank Sta=9824.019,10256.03
Exp/Cntr=0.3,0.1

Type RM Length L Ch R = 1 ,1596.329,86.717200,86.717200,86.717200
XS GIS Cut Line= 6
1264228.02278072615987.171358451 1264163.3179068615891.327357545
1264129.11825591615826.8307234791264122.41372967615820.126197219
1264085.50705153615807.5973050451263929.12669262615785.928425223
#Sta/Elev= 30
9824.04891.807199836.21190.895919848.08688.832989859.96287.544299872.08486.73769
9887.67184.014619901.40284.032329907.464 83.77399950.32279.748239968.91776.51615
9976.35574.787129987.51172.953149998.66872.4599610009.7473.7242710018.2675.37137
10022.1875.7290910036.32 76.243610046.7175.79068 10063.776.5665910070.3277.42933
10086.8877.1054710090.1977.2499310100.1378.4103710106.7578.78843   1012078.71716
10129.9479.2296710153.1379.0695910159.75  78.72910206.1278.1084210219.0878.32297
#Mann= 3 , 0 , 0
9824.048   0.045       09824.048   0.045       010219.08   0.045       0
#XS Ineff= 2 , 0
       0                10055.77       0
Bank Sta=9824.048,10219.08
Exp/Cntr=0.3,0.1

Type RM Length L Ch R = 1 ,1509.611,97.225300,97.225300,97.225300
XS GIS Cut Line= 6
1264319.04956079 615930.264623211264249.01514921615831.568658069
1264227.54702702615809.1592103391264195.38364851615787.076735675
 1264168.9270398615771.822522432 1264008.3367621615734.930161327
#Sta/Elev= 30
9824.08483.463319858.50880.84951 9870.7580.510849881.69979.073189899.09377.47959
    991976.896029926.57776.360119952.67773.072769970.77872.101619992.45469.54363
    999969.2896110015.1969.9112810035.0571.6219710046.3473.0359310056.43 73.1915
 10059.872.6697810066.5372.3881310086.73 72.7027 10100.273.2812110103.5673.94031
 10110.7 74.540110120.3974.3308210133.86 74.852210143.9674.8365610154.6675.69136
10180.9975.3810310187.7275.8114210194.4575.7005610201.1876.76688 10210.576.55223
#Mann= 3 , 0 , 0
9824.084  0.0627       09824.084  0.0627       0 10210.5  0.0627       0
#XS Ineff= 2 , 0
       0                10049.23       0
Bank Sta=9824.084,10210.5
Exp/Cntr=0.3,0.1

Type RM Length L Ch R = 1 ,1412.386,76.209200,76.209200,76.209200
XS GIS Cut Line= 6
1264326.26210928615887.9249529991264299.89299658615804.965895772
1264289.27469257615760.5992975531264275.77415067615726.762368158
1264229.69092873615699.1228696851264099.48259538615674.166272447
#Sta/Elev= 30
9842.537 77.12629872.90873.434989879.793  72.9699897.00670.818279907.334 70.2413
9917.66270.470569927.98969.210069934.78168.999979951.66967.661539975.21163.76274
9989.38762.714379996.45262.8562110003.5263.5609210011.6465.54887 10014.565.93515
10018.33 65.534810028.8667.6015910041.2867.2815310048.9368.6821710060.7569.74881
10081.08 70.145810101.1269.5178910114.4968.1635610131.1968.4392410134.5368.60708
10139.8969.6486810147.8970.5299210154.5770.6620510171.2871.7629710197.9672.45639
#Mann= 3 , 0 , 0
9842.537  0.0527       09842.537  0.0527       010197.96  0.0527       0
#XS Ineff= 2 , 0
       0                10045.31       0
Bank Sta=9842.537,10197.96
Exp/Cntr=0.3,0.1

Type RM Length L Ch R = 1 ,1336.177,86.717200,86.717200,86.717200
XS GIS Cut Line= 6
1264440.04118752615865.4117270861264405.75435597615813.518663451
1264381.31226671615771.8631527131264327.54764009615664.119877324
1264304.56072038615639.4440502081264143.97044259615596.041272447
#Sta/Elev= 30
9824.02475.269949847.461 72.23989855.32671.679299882.44268.076419898.17767.35535
9914.51965.501229932.41364.712949943.53163.018019969.31962.12458 9977.1862.81783
9984.39361.590449991.60559.323149995.10858.7626110002.4258.4534210009.7258.80996
10024.3161.3045610035.2662.2377510057.4862.18775 10067.163.0430710076.7362.28428
10088.6662.4233310107.4363.0032110124.4264.5811110141.4165.09644   1015563.48605
   1017263.3318610188.9963.7107910199.1964.8076610212.7865.5729810255.0166.69777
#Mann= 3 , 0 , 0
9824.024  0.0584       09824.024  0.0584       010255.01  0.0584       0
#XS Ineff= 2 , 0
       0                10071.42       0
Bank Sta=9824.024,10255.01
Exp/Cntr=0.3,0.1

Type RM Length L Ch R = 1 , 1249.46,86.717200,86.717200,86.717200
XS GIS Cut Line= 6
1264529.99789971615805.8335003111264476.38170281 615738.49730739
1264424.00304347615666.6486933831264422.71665928615665.117283687
1264384.42183149615617.959675208 1264295.8801648615552.855508551
#Sta/Elev= 30
9824.01179.50708 9839.9576.405059846.31475.558389856.84872.792279873.50169.19608
 9888.4566.497779907.051   63.739919.32862.208219959.60957.96384 9976.1756.92875
 9992.4152.60968 9996.4752.4804510000.6253.1826610014.1956.5231410017.5356.98111
10029.8157.1094510038.6657.9564510045.4258.0322310050.6358.4394210073.4157.73914
10077.4857.8385910086.8758.7171210101.9158.9248410114.1358.74691 10118.259.49369
10130.4260.8493310136.7261.1811410158.9259.9121510167.0760.7827810171.6560.66846
#Mann= 3 , 0 , 0
9824.011  0.0645       09824.011  0.0645       010171.65  0.0645       0
#XS Ineff= 2 , 0
       0                 10051.2       0
Bank Sta=9824.011,10171.65
Exp/Cntr=0.3,0.1

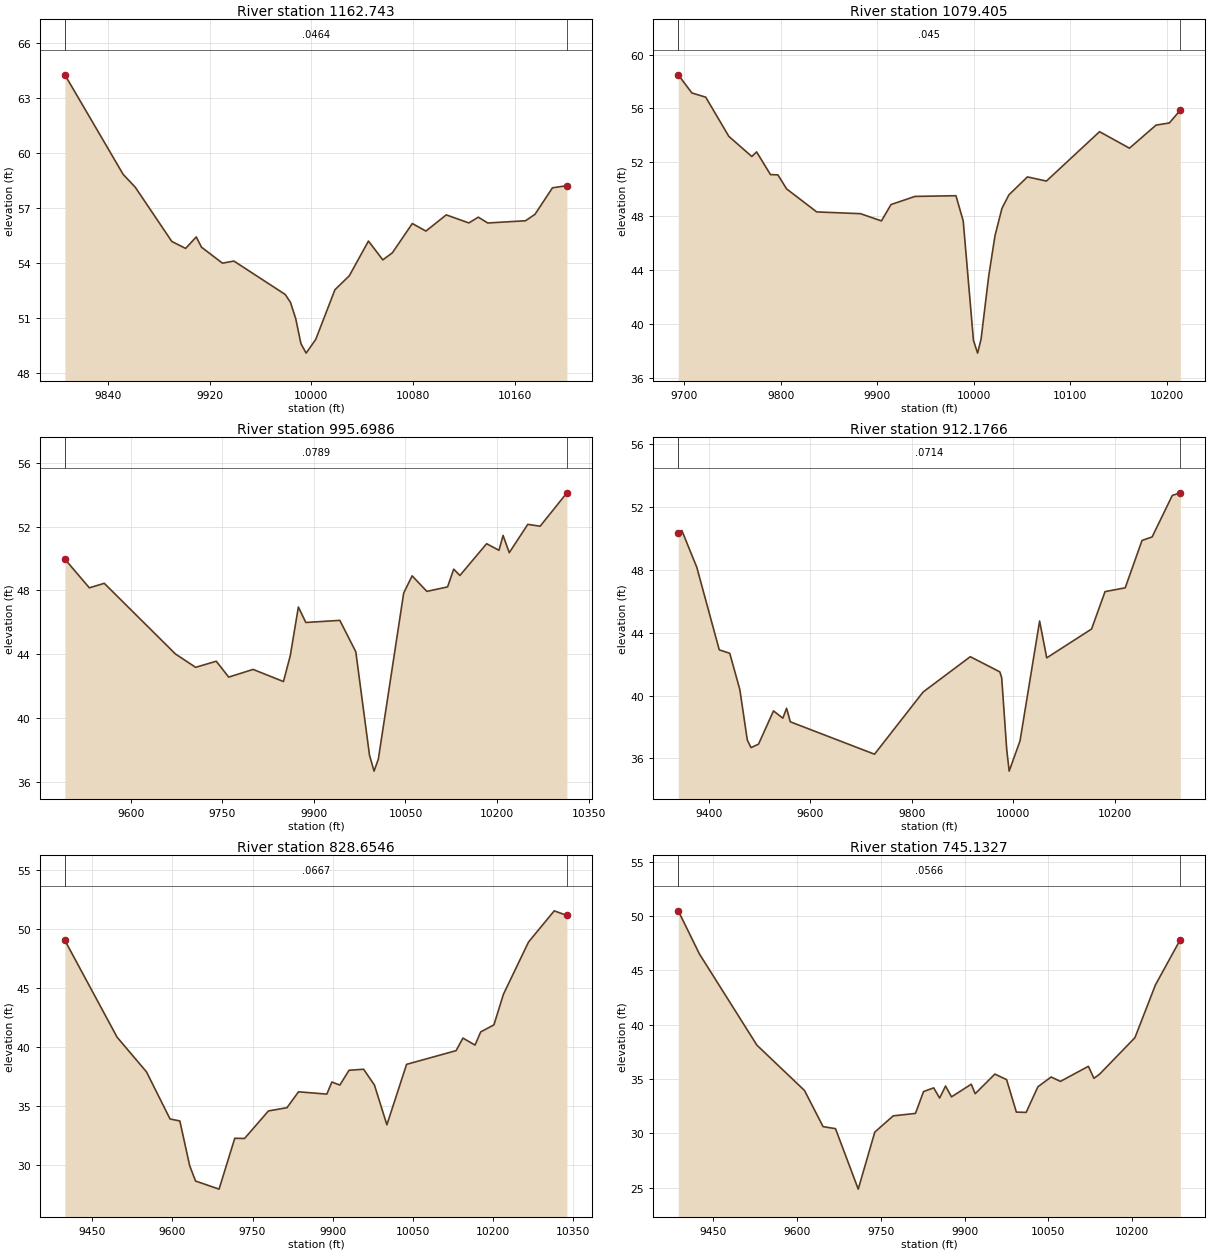
Type RM Length L Ch R = 1 ,1162.743,83.337600,83.337600,83.337600
XS GIS Cut Line= 6
1264641.62669259 615739.74786967 1264582.5989148615683.324258551
1264497.11090147615618.4521331341264495.44680083615617.342732802
1264392.49474815615559.1923141031264316.71349815615519.001341879
#Sta/Elev= 30
9806.11264.263049851.96758.839459861.46458.142589890.26455.183749901.11954.80657
9909.46355.433749913.58154.875149930.05654.005279939.11154.118129979.47852.29886
9983.59651.868679987.71550.984919991.83349.617389995.91549.10381 10003.549.85529
10018.5752.5560710029.8853.3175410044.9555.2089610056.2554.1834910063.7954.57134
10079.4656.1632510090.17 55.752210106.1556.6349910123.9556.1951710131.3856.51048
10138.8156.1927310168.5256.3144310175.9456.6633410189.7258.10808 10201.158.22575
#Mann= 3 , 0 , 0
9806.112  0.0464       09806.112  0.0464       0 10201.1  0.0464       0
#XS Ineff= 2 , 0
       09936.181        10071.76       0
Bank Sta=9806.112,10201.1
Exp/Cntr=0.3,0.1

Type RM Length L Ch R = 1 ,1079.405,83.706300,83.706300,83.706300
XS GIS Cut Line= 5
1264771.71928522615743.9543222041264596.37206298615579.023766637
1264538.48414731615546.6394782071264484.36748585615522.378404692
1264337.94295111615476.081846997
#Sta/Elev= 30
9693.96158.494699708.03857.149049722.40456.834659746.34753.922429770.13152.43066
9775.07852.771439789.44451.086779797.15551.063689806.16450.022349837.329 48.3143
9882.73348.181959904.36947.644469914.26248.859779939.18149.465469981.54849.51618
9989.06647.63899 9999.6638.7708210003.9737.8259310007.5638.8729510015.4443.53482
10021.9546.5389910029.1448.5703910036.3349.5765910055.5450.9139410075.2150.60387
10130.2654.2726210161.2353.0468310188.7654.7607510202.5254.9183610213.8955.87418
#Mann= 3 , 0 , 0
9693.961   0.045       09693.961   0.045       010213.89   0.045       0
#XS Ineff= 2 , 0
       09937.718         10082.8       0
Bank Sta=9693.961,10213.89
Exp/Cntr=0.3,0.1

Type RM Length L Ch R = 1 ,995.6986,83.522000,83.522000,83.522000
XS GIS Cut Line= 6
1264974.84428522615759.5793222041264624.65620649 615501.64023076
 1264561.6969201615467.3501604651264559.88600218 615466.50129275
1264474.26558152615438.2721752231264256.81766483615387.707939118
#Sta/Elev= 30
9492.378 49.96319532.40848.162629556.85748.446529673.28944.014579706.48143.17284
9740.22143.557259760.59542.560649800.52643.04273 9850.2442.282319861.37943.89834
9874.68946.959089886.91345.988099942.57546.120819968.72644.147799991.14137.65905
9998.61336.6591610005.6437.41872 10047.147.8349310060.9248.91601 10085.1 47.9401
10118.9348.2204510129.0449.3364410139.1448.9374810182.9350.9332310203.1450.51776
10209.8851.4512210219.9850.36842 10250.352.1460310270.5152.03015 10314.454.12524
#Mann= 3 , 0 , 0
9492.378  0.0789       09492.378  0.0789       0 10314.4  0.0789       0
#XS Ineff= 2 , 0
       09920.271        10060.24       0
Bank Sta=9492.378,10314.4
Exp/Cntr=0.3,0.1

Type RM Length L Ch R = 1 ,912.1766,83.522000,83.522000,83.522000
XS GIS Cut Line= 5
1265188.38595188615695.3432110851264601.55338749615394.168028355
1264599.71145296615393.3887484071264501.39320618615356.226337433
1264280.68919259615323.688841879
#Sta/Elev= 30
9339.39550.355089346.44450.501039375.94648.157489420.19842.907129440.87442.68848
9460.76240.383569475.51337.167249482.88936.685889497.63936.906769527.14139.02212
9545.57938.558599552.95539.18969 9560.33 38.32699726.27636.266449822.15640.22529
9915.10942.471369973.35141.505459977.03841.137079986.962 36.56239991.78935.18964
10013.2237.11927 10051.844.7392210065.8342.3981110154.25 44.233110180.7846.61094
10220.5746.8543610253.7349.8686210273.6350.0904910313.4352.73408 10329.252.89772
#Mann= 3 , 0 , 0
9339.395  0.0714       09339.395  0.0714       0 10329.2  0.0714       0
#XS Ineff= 2 , 0
       09922.633        10056.14       0
Bank Sta=9339.395,10329.2
Exp/Cntr=0.3,0.1

Type RM Length L Ch R = 1 ,828.6546,83.521900,83.521900,83.521900
XS GIS Cut Line= 6
1265171.02484074615556.4543222041264757.26364881615354.239186645
1264676.28635985615326.3535448761264499.17112491615280.932011083
1264408.31065178615243.9257384691264308.10659346 615193.16767709
#Sta/Elev= 30
9398.77449.062369496.49840.854539551.56437.913099595.61833.919929613.97333.75043
9632.32929.968369643.34228.656899687.39527.969899716.76432.283319735.11932.26492
9779.80834.599829814.542 34.87659836.08136.222819889.16836.027969898.48637.05214
9913.49636.795439930.69838.049229957.99738.136299978.22636.7988610001.5633.42457
10038.4238.5508610131.1139.7142910143.8940.7792110166.5440.1857310177.16 41.3015
10201.9641.9027110219.6744.4885710266.7648.9283110314.8651.57023 10338.6 51.1764
#Mann= 3 , 0 , 0
9398.774  0.0667       09398.774  0.0667       0 10338.6  0.0667       0
#XS Ineff= 2 , 0
       09937.906        10046.97       0
Bank Sta=9398.774,10338.6
Exp/Cntr=0.3,0.1

Type RM Length L Ch R = 1 ,745.1327,77.972400,77.972400,77.972400
XS GIS Cut Line= 6
1265195.33039632615499.1626555471264867.36671475615328.025677964
1264787.07533875615290.5918811111264700.28716412615255.665368065
1264606.75474364615221.1160379651264363.99944821615177.677807987
#Sta/Elev= 30
9387.59450.471189425.37346.511979528.32338.113899613.43833.948779646.744  30.621
9668.94830.432339709.65524.87145 9739.2630.118229772.23831.612519812.05731.83674
9826.53633.847799844.63534.185249855.279 33.25059865.889 34.35429876.49833.35841
9911.864 34.52189918.93733.649549954.14635.455019975.13934.943379992.63331.95672
10010.1231.9313710031.0934.2836310054.8135.1868410071.4734.7821710121.4736.16965
10131.4635.0654410141.4635.4406910204.7938.8031810241.4543.6539810285.99 47.8259
#Mann= 3 , 0 , 0
9387.594  0.0566       09387.594  0.0566       010285.99  0.0566       0
#XS Ineff= 2 , 0
       09926.868        10049.86       0
Bank Sta=9387.594,10285.99
Exp/Cntr=0.3,0.1

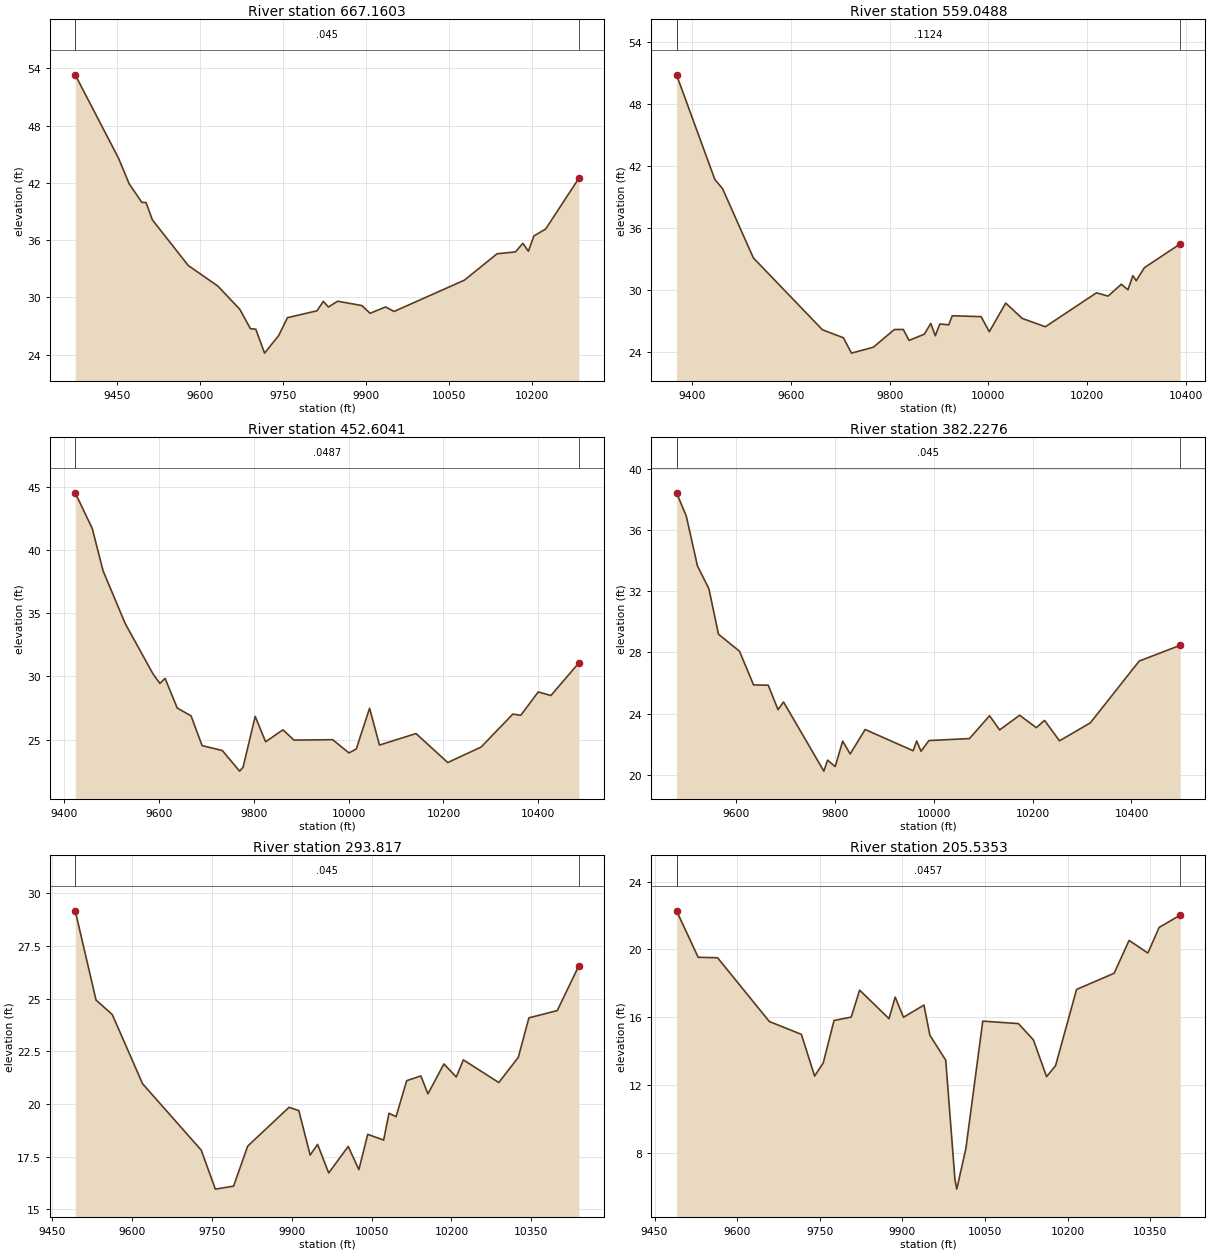
Type RM Length L Ch R = 1 ,667.1603,108.111500,108.111500,108.111500
XS GIS Cut Line= 6
1265226.58039629615454.0237666371264835.71913305615220.625574455
1264762.41987368 615183.954462261264717.66198522615167.517351896
1264544.12097597615170.0823218821264393.29632321615142.955585778
#Sta/Elev= 30
9373.76253.327729452.30144.575229471.40741.913279494.33539.964639501.97739.94544
9513.44138.130689578.40233.34534  9631.931.195769671.76828.753659690.96626.72505
9700.68326.670089716.56324.16247 9742.1626.005359758.00127.876229811.49928.59904
9822.96329.588429832.15128.996779848.884 29.60399892.90629.14448 9907.5828.33746
9935.73429.005039951.02728.5309810078.3531.8072210137.5334.5759910170.87 34.7715
 10184.235.67022 10194.234.84271 10204.236.44071 10225.537.1681310285.6542.49194
#Mann= 3 , 0 , 0
9373.762   0.045       09373.762   0.045       010285.65   0.045       0
#XS Ineff= 2 , 0
       09946.676        10069.29       0
Bank Sta=9373.762,10285.65
Exp/Cntr=0.3,0.1

Type RM Length L Ch R = 1 ,559.0488,106.444700,106.444700,106.444700
XS GIS Cut Line= 6
1265247.41372964615372.4265444281264855.68441078615120.799185574
1264782.38515148 615084.128073351264717.92381206615063.112318933
1264664.23616382615054.6170161521264320.33039632614985.273766652
#Sta/Elev= 30
9368.28750.860729445.89840.720129461.49539.838179523.88533.130779663.908 26.1647
9706.40125.393129722.754 23.90469767.10624.476579809.59926.192229827.81126.19687
9839.38825.135769870.54725.74446 9883.4126.784879892.54525.586569901.75326.72538
9919.89926.649799926.89927.523359985.45527.4385510002.01 25.976410035.2928.75384
10068.7427.26717 10115.626.4577810219.3529.7494210242.7829.4269510269.5530.57551
10282.9430.0433710292.9831.4062410299.6830.9210910316.4132.1856610388.9434.48608
#Mann= 3 , 0 , 0
9368.287  0.1124       09368.287  0.1124       010388.94  0.1124       0
#XS Ineff= 2 , 0
       09924.471        10047.27       0
Bank Sta=9368.287,10388.94
Exp/Cntr=0.3,0.1

Type RM Length L Ch R = 1 ,452.6041,70.376500,70.376500,70.376500
XS GIS Cut Line= 6
1265273.45539629615294.3015444281264827.27484074615075.551544428
1264795.71540922615036.9097176341264789.62916073615018.644776478
1264762.23557821614980.201327816 1264323.8026185614888.051544443
#Sta/Elev= 30
9423.78344.517259459.741 41.69189482.55138.345939529.16534.182019587.62830.21442
9602.24429.447529613.20529.850119638.78327.511659668.01426.885049691.23124.53914
9733.78524.148459770.32422.519799777.63222.833989803.20926.845669825.133 24.8405
9861.67225.784279885.00524.972219966.57625.0054910000.8123.9566610016.1824.26349
 10044.327.4903510065.2124.5808710142.1825.49036 10209.123.1984610279.3724.42173
10346.2927.0277410363.0226.9319410399.8328.77754 10426.628.4975910485.5431.07752
#Mann= 3 , 0 , 0
9423.783  0.0487       09423.783  0.0487       010485.54  0.0487       0
#XS Ineff= 2 , 0
       09939.486        10091.53       0
Bank Sta=9423.783,10485.54
Exp/Cntr=0.3,0.1

Type RM Length L Ch R = 1 ,382.2276,88.410600,88.410600,88.410600
XS GIS Cut Line= 6
 1265276.9276185615223.1209888611265006.94930074615054.072293803
 1264870.1721462614977.7763160471264791.95510089614941.178566203
1264677.82460928614911.3624529841264346.37206295614839.440433323
#Sta/Elev= 30
9479.92238.417469499.63936.892339522.111 33.64629545.33732.150399564.69229.18125
9607.27228.066539635.64425.867829665.33625.84998  9685.124.252599696.30324.75165
9777.83120.235319785.33420.954489800.76620.53276 9815.9122.198889831.05321.35768
 9861.3422.955629958.36621.568289965.604  22.2089974.36521.531869990.36422.23376
 10072.322.3608410112.9923.8536810133.34 22.929610173.8823.8867410207.4523.07718
10224.2423.5487910254.4522.2166110316.7423.38764 10415.627.4259710498.6428.45639
#Mann= 3 , 0 , 0
9479.922   0.045       09479.922   0.045       010498.64   0.045       0
#XS Ineff= 2 , 0
       09889.244        10111.07       0
Bank Sta=9479.922,10498.64
Exp/Cntr=0.3,0.1

Type RM Length L Ch R = 1 , 293.817,88.281700,88.281700,88.281700
XS GIS Cut Line= 6
1265301.23317406615106.8015444281265004.98996633614934.167241126
  1264931.690707614897.4961289021264888.28002742614881.372079939
1264867.22936758614876.4803744851264420.27252591 614802.24786967
#Sta/Elev= 30
9493.406 29.16359532.54724.926099562.92524.241839619.88420.955799730.00417.80335
9756.58515.95137 9790.7616.092529817.34117.995329895.02219.837369913.365 19.6769
9934.58817.569159948.58718.074429969.397 16.7191 10006.117.9801310026.0616.87572
10042.6918.5535810072.6318.2807310082.6119.5526710095.91 19.391710115.8721.10028
10142.4921.3239510155.7920.4739110185.7321.8939910209.0221.2756310222.3222.08692
10288.8621.0116210325.4522.2077110345.4124.0824610398.6324.4279310439.2526.55984
#Mann= 3 , 0 , 0
9493.406   0.045       09493.406   0.045       010439.25   0.045       0
#XS Ineff= 2 , 0
       09877.057        10119.35       0
Bank Sta=9493.406,10439.25
Exp/Cntr=0.3,0.1

Type RM Length L Ch R = 1 ,205.5353,88.281700,88.281700,88.281700
XS GIS Cut Line= 6
1265313.38595188615047.7737666521265052.13725322614877.375932738
1264937.74597278614811.7662520111264897.27814913614793.452968374
 1264859.4760336614787.0836327521264485.76731759614682.412800208
#Sta/Elev= 30
9490.04522.27998 9529.2619.538189564.51419.510169658.52215.747629716.71214.98792
9740.733 12.52819756.44813.304959776.03315.807319807.22616.006559822.47917.59932
9875.818 15.9149 9887.0617.189599902.04815.997399939.29916.716969950.10314.93446
9978.864 13.46319995.5586.4296159998.8975.85269810015.488.25921810046.1115.76869
10110.85  15.625 10138.114.6600310161.95  12.49310178.2113.1321910216.4717.63949
10284.6118.5933210311.8620.5345410345.9419.7889810366.3821.29982 10404.722.02595
#Mann= 3 , 0 , 0
9490.045  0.0457       09490.045  0.0457       0 10404.7  0.0457       0
#XS Ineff= 2 , 0
       09862.074        10079.91       0
Bank Sta=9490.045,10404.7
Exp/Cntr=0.3,0.1

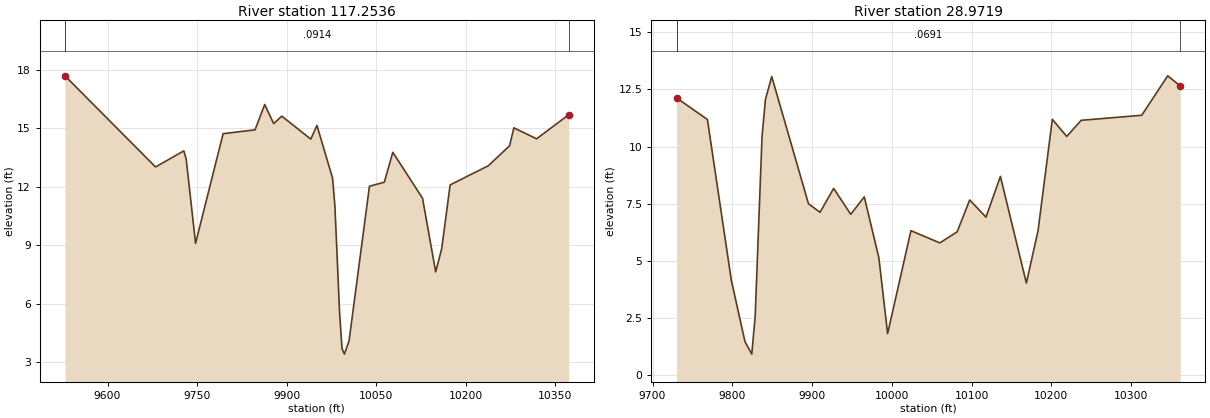
Type RM Length L Ch R = 1 ,117.2536,88.281700,88.281700,88.281700
XS GIS Cut Line= 6
1265311.64984074614995.6904333081265089.01800916614847.028318942
1265018.20842546614796.3877660481264946.73468339614737.305808023
1264907.35215533614710.4036781341264585.59370652614574.990925223
#Sta/Elev= 30
9528.65517.68654 9680.4713.013119727.81113.839169731.75613.432559747.5369.098917
9793.737 14.72139847.27914.917559863.41316.215459878.455 15.23719892.10315.61772
9940.67914.443129950.97815.142399977.15812.443519981.11510.989739989.0285.486152
9992.9853.7085679996.9423.41886310004.824.09898910038.9812.02535 10063.912.23315
10078.1413.7652910127.9711.4106310149.987.63507910160.018.81263710174.2412.09496
10238.32 13.076810273.9114.1037810281.0315.0200810319.1414.4576810372.9415.69139
#Mann= 3 , 0 , 0
9528.655  0.0914       09528.655  0.0914       010372.94  0.0914       0
#XS Ineff= 2 , 0
       09876.324        10063.96       0
Bank Sta=9528.655,10372.94
Exp/Cntr=0.3,0.1

Type RM Length L Ch R = 1 , 28.9719,0.000000,0.000000,0.000000
XS GIS Cut Line= 4
1265205.28410003  614836.55053171265025.30724818614685.928425223
1264968.88363704614658.1506474321264665.93224818614517.525647432
#Sta/Elev= 30
9730.08812.132969768.85711.185979798.8044.1565679815.9171.4670439824.4730.918427
9828.7522.5819919837.30810.419879841.586 12.06429849.51613.064139895.5237.502494
9910.0377.124913 9927.158.1700419948.5417.0376859965.5267.798937 9983.815.135971
9994.7811.81353810024.046.32090410060.255.78602310081.95  6.269310097.697.664937
10118.126.912113 10136.28.69500510168.764.028283 10183.46.32236910201.3111.19243
 10219.410.4454510237.4811.1503810313.4411.3720310345.9913.0972710361.6712.65654
#Mann= 3 , 0 , 0
9730.088  0.0691       09730.088  0.0691       010361.67  0.0691       0
#XS Ineff= 2 , 0
       09910.109        10092.52       0
Bank Sta=9730.088,10361.67
Exp/Cntr=0.3,0.1